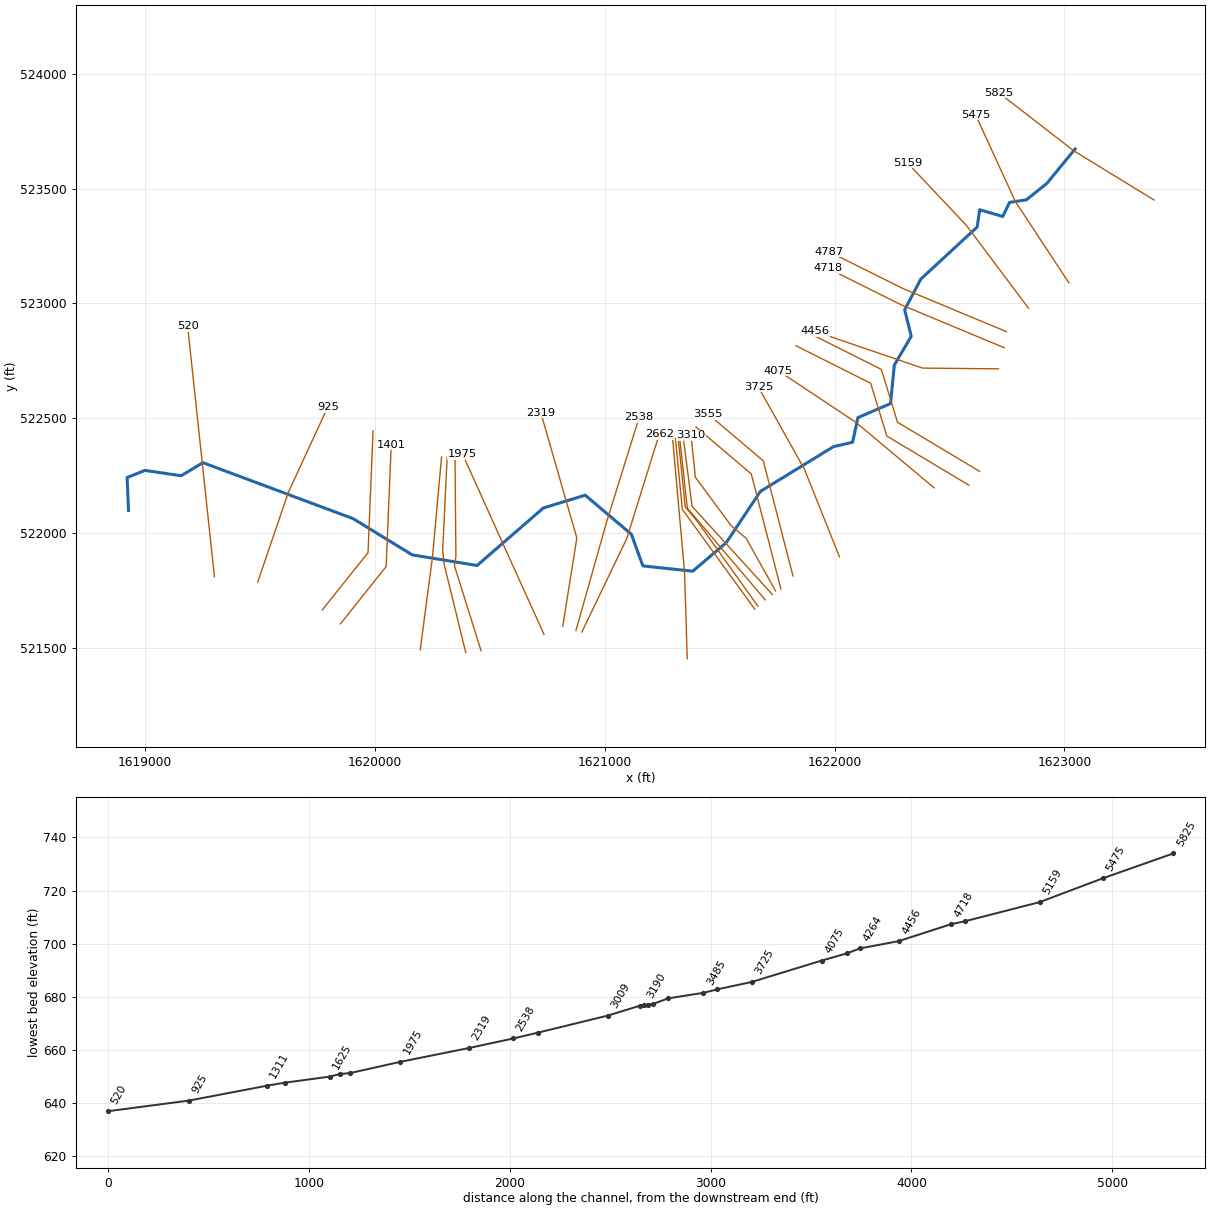
--- ParrsRn.prj (project) ---

Proj Title=ParrsRn
Current Plan=p01
Default Exp/Contr=0,0
English Units
Geom File=g01
Flow File=f01
Plan File=p01
Background Map Layer=Inundation Boundary (P100yr Value_0)
BEGIN DESCRIPTION:
---------- MODELED AS PART OF WVEM CTP PROGRAM, 2025----------
Stream Name: Parrs Run
Flood Zone: AFH
Marshall County, WV
HEC-RAS Version: RAS 6.6
Vertical Datum: NAVD88
Projection: NAD 1983 StatePlane West Virginia N FIPS 4701 (US Feet)
Terrain: 1-meter West Virginia FEMA R3 South Central (collected 2018-2019)
Land Use: 2024 NLCD
Hydrologic Method:
Duda et al., "Estimation of magnitude and frequency of floods for rural, unregulated streams in and near Virginia and West Virginia." September 8, 2025.
Additional Model Notes:
None
END DESCRIPTION:
DSS File=dss
DSS Export Rating Curves= 0
DSS Export Rating Curve Sorted= 0
DSS Export Volume Flow Curves= 0
DXF OffsetX= 0
DXF OffsetY= 0
DXF ScaleX= 0
DXF ScaleY= 0

--- ParrsRn.p01 (plan) ---

Plan Title=Floodplain
Program Version=6.60
Short Identifier=Floodplain
Geom File=g01
Flow File=f01
Subcritical Flow
K Sum by GR= 0
Std Step Tol= 0.01
Critical Tol= 0.01
Num of Std Step Trials= 20
Max Error Tol= 0.3
Flow Tol Ratio= 0.001
Split Flow NTrial= 30
Split Flow Tol= 0.02
Split Flow Ratio= 0.02
Log Output Level= 0
Friction Slope Method= 1
Unsteady Friction Slope Method= 2
Unsteady Bridges Friction Slope Method= 1
Parabolic Critical Depth
Global Vel Dist= 0 , 0 , 0
Global Log Level= 0
CheckData=False
Encroach Param=-1 ,0,0, 0
Flow Ratio Tolerance=0.1
Flow Ratio Min Ratio=0.5
Flow Ratio Max Ratio=4
Flow Ratio Max Iterations= 10
Computation Interval=0.1SEC
Output Interval=1SEC
Instantaneous Interval=Max Profile
Mapping Interval=1HOUR
Computation Time Step Use Courant=        0
Computation Time Step Use Time Series=    0
Computation Time Step Count To Double=0
Computation Time Step Max Doubling=0
Computation Time Step Max Halving=0
Computation Time Step Residence Courant=0
Run HTab= 0
Run UNet= 0
Run Sediment= 0
Run PostProcess= 0
Run WQNet= 0
Run RASMapper=-1
UNET Theta= 0
UNET Theta Warmup= 0
UNET ZTol= 0
UNET ZSATol= 0
UNET MxIter= 0
UNET Max Iter WO Improvement= 0
UNET MaxInSteps= 0
UNET DtIC= 0
UNET DtMin= 0
UNET MaxCRTS= 0
UNET WFStab= 0
UNET SFStab= 0
UNET WFX= 1
UNET SFX= 1
UNET Gravity=32.17405
UNET 1D Methodology=Finite Difference
UNET DSS MLevel= 1
UNET Pardiso=0
UNET DZMax Abort= 0
UNET Use Existing IB Tables= 0
UNET Froude Reduction=False
UNET Froude Limit= 0
UNET Froude Power= 0
UNET D1 Cores= 0
UNET WindReference=Eulerian
UNET WindDragFormulation=Hsu (1988)
UNET D2 Coriolis=0
UNET D2 Cores= 0
UNET D2 Theta= 1
UNET D2 Theta Warmup= 1
UNET D2 Z Tol= 0.01
UNET D2 Volume Tol= 0.01
UNET D2 Max Iterations= 20
UNET D2 Advanced Convergence=0
UNET D2 WS Max Tol=0.15
UNET D2 WS RMS Tol=0.002
UNET D2 WS Stall Tol=1
UNET D2 Equation= 0
UNET D2 RampUpFraction=0.1
UNET D2 TimeSlices= 1
UNET D2 Turbulence Formulation=Non-Conservative (original)
UNET D2 Eddy Viscosity=0.3
UNET D2 Transverse Eddy Viscosity=0.1
UNET D2 Smagorinsky Mixing=0
UNET D2 BCVolumeCheck=0
UNET D2 Cores=0
UNET D2 SolverType=PARDISO (Direct)
UNET D2 Minimum Iterations= 3
UNET D2 Maximum Iterations= 30
UNET D2 Restart Number= 10
UNET D2 Relaxation Coeff=1.3
UNET D2 SOR Precondition Iterations= 10
UNET D2 ILUT Maximum Fill= 8
UNET D2 ILUT Tolerance=1E-08
UNET D2 Convergence Tolerance=0.00001
PS Theta= 1
PS WS Tol= 0.01
PS Volume Tol= 0.01
PS Max Iterations= 20
PS Equation= 0
PS Advance Time Step=-1
PS Target Courant=0.9
PS Time Slices= 1
PS Iterate With 2D=0
PS Project Initial WSE from DS=-1
PS Ramp Up Initial WSE from US=-1
PS Cores=0
UNET D1D2 MaxIter= 0
UNET D1D2 ZTol=0.01
UNET D1D2 QTol=0.1
UNET D1D2 MinQTol=1
DSS File=dss
Write IC File= 0
Write IC File at Fixed DateTime=0
Write IC File at Sim End=0
Echo Input=False
Echo Parameters=False
Echo Output=False
Write Detailed= 0
HDF Write Warmup=0
HDF Write Time Slices=0
HDF Flush=0
HDF Compression= 1
HDF Chunk Size= 1
HDF Spatial Parts= 1
HDF Use Max Rows=0
HDF Fixed Rows= 1
Calibration Method= 0
Calibration Iterations= 20
Calibration Max Change=0.05
Calibration Tolerance=0.2
Calibration Maximum=1.5
Calibration Minimum=0.5
Calibration Optimization Method= 1
WQ AD Non Conservative
WQ ULTIMATE=-1
WQ Max Comp Step=1HOUR
WQ Output Interval=15MIN
WQ Output Selected Increments= 0
WQ Create Restart=0
WQ Fixed Restart=0
WQ System Summary=0
WQ Write To DSS=0
Sorting and Armoring Iterations= 10
XS Update Threshold= 0.02
Bed Roughness Predictor= 0
Processes Affected by Predictor=Sediment Only
Hydraulics Update Threshold= 0.02
Energy Slope Method= 1
Volume Change Method= 1
Sediment Retention Method= 0
Sediment TS Multiplier= 1
Warm Up Method= 0
XS Weighting Method= 0
Number of US Weighted Cross Sections= 1
Number of DS Weighted Cross Sections= 1
Upstream XS Weight=0
Main XS Weight=1
Downstream XS Weight=0
Number of DS XS's Weighted with US Boundary= 1
Upstream Boundary Weight= 1
Weight of XSs Associated with US Boundary= 0
Number of US XS's Weighted with DS Boundary= 1
Downstream Boundary Weight= 0.5
Weight of XSs Associated with DS Boundary= 0.5
Percentile Method= 0
Sediment Output Level= 3
Mass or Volume Output= 0
Output Increment Type= 1
Profile and TS Output Increment= 1
Transport Output Increment 1
XS Output Flag= 0
XS Output Increment= 10
Read HDF5 Sediment Hotstart= 0
Sediment Hotstart Type= 0
Write Gradation File= 0
Read Gradation Hotstart= 0
Write HDF5 File= 1
Write Binary Output= 1
Write DSS Sediment File= 0
DSS Sediment Output Type= 1
SV Curve= 0
Specific Gage Flag= 0
Subcell Erosion Methods= 0
Subcell Deposition Methods= 0
Advection Scheme= 1
Matrix Solver= 0
Implicit Weighting Factor= 1
Maximum Outer Loop Convergence Iterations= 5
Convergence Maximum Absolute= 0.001
Convergence RMSE= 0.0001
Grain Fractions Max Abs Error= 0.001
Max Subgrid Regions= 1
Max Subgrid Length Scale= 3.402823E+38
Initial Layer Thickness= 3
Min Layer Thickness= 0.1
Max Layer Thickness= 6
Number of Layers= 5

--- ParrsRn.f01 (steady flow) ---

Flow Title=Flow
Program Version=6.60
Number of Profiles= 1
Profile Names=P100yr
River Rch & RM=ParrsRn,Main,5825
     778
River Rch & RM=ParrsRn,Main,1401
     862
Boundary for River Rch & Prof#=ParrsRn,Main            , 1
Up Type= 0
Dn Type= 3
Dn Slope=0.021594
DSS Import GetInterval= 0
DSS Import GetPeak= 0
DSS Import FillOption= 0

--- ParrsRn.g01 (geometry) ---

Geom Title=Geometry
Program Version=6.60

River Reach=ParrsRn         ,Main
Reach XY= 30
     1623046.517      523672.136     1622924.136      523523.034
     1622834.821      523451.164     1622761.055      523439.407
     1622731.473      523378.347     1622631.158       523407.55
     1622620.148      523332.444        1622375.      523106.018
     1622304.593      522972.148     1622333.333      522856.944
     1622259.722      522731.944     1622243.209      522564.167
     1622101.126      522502.876     1622078.095      522395.783
     1621994.801      522376.591     1621676.979      522181.983
     1621528.094      521958.616     1621382.571      521834.604
     1621165.316      521857.635     1621115.416      521995.435
     1620914.436      522165.462     1620732.156      522109.697
     1620443.752       521859.37     1620161.489      521905.799
     1619904.529      522063.268     1619250.825      522306.995
     1619156.064      522250.019     1618998.328      522273.409
     1618920.984      522242.246     1618926.958       522098.88

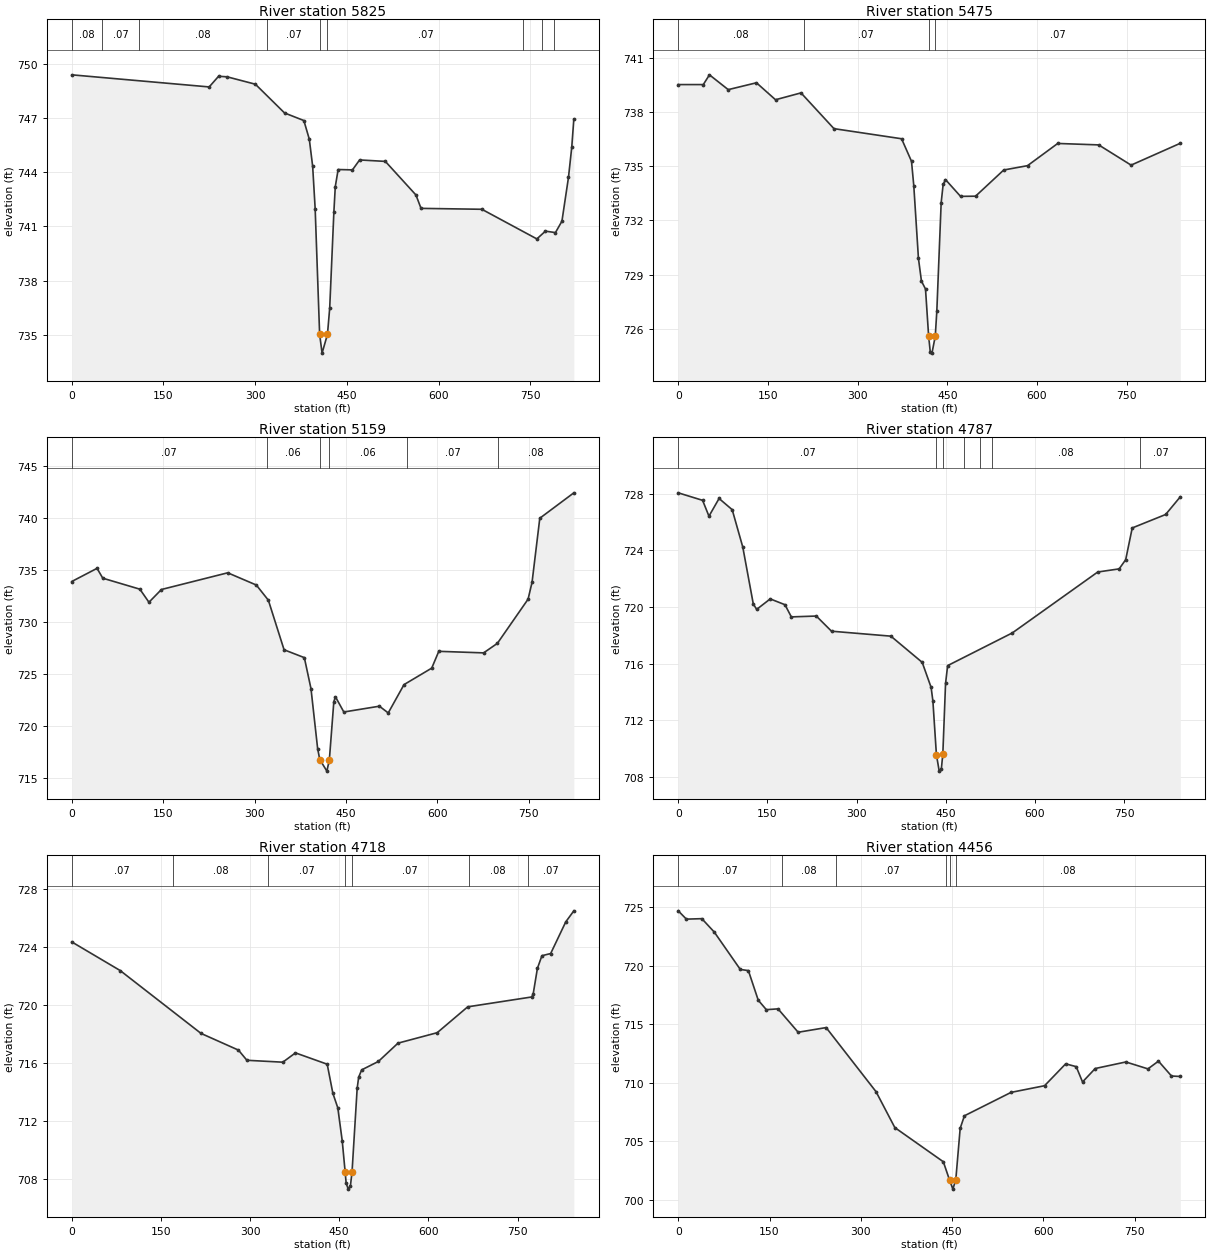
Type RM Length L Ch R = 1 ,5825    ,350.7,350,346.5
XS GIS Cut Line= 3
     1623390.052      523449.961     1623041.447      523663.519
      1622715.27      523916.158
#Sta/Elev= 30
       0  749.39   224.8  748.72   240.2  749.31   254.1  749.28   300.4  748.87
   348.1  747.28   379.7  746.86   388.6  745.83   394.1  744.33   398.2  741.98
   405.5735.0367   409.5  733.99   418.3735.0256     422  736.49   428.8  741.79
   431.1   743.2   435.8  744.15   459.2  744.13   470.9  744.68     513   744.6
   563.1  742.74   571.4     742   670.9  741.95   760.9  740.31   774.9  740.74
   791.3  740.66   801.9  741.29   812.6  743.71     818  745.39   821.4  746.95
#Mann= 9 ,-1,0
       0     .08       0      50     .07       0     110     .08       0
     320     .07       0   405.5    .045       0   418.3     .07       0
  738.82     .06       0  768.82     .07       0  788.82     .06       0
Bank Sta=405.5,418.3
XS Rating Curve= 0 ,0
Exp/Cntr=0.3,0.1

Type RM Length L Ch R = 1 ,5475    ,310,315.6,314.3
XS GIS Cut Line= 3
      1623019.24      523089.631     1622786.013      523444.127
     1622612.927      523821.546
#Sta/Elev= 30
       0  739.52    41.9  739.52    52.2  740.06    83.6  739.24   130.8  739.62
   162.7  738.68   205.3  739.06   260.4  737.08   373.5  736.52   390.1  735.27
   393.9  733.92   401.7  729.89   406.7  728.64   413.5   728.2   418.7725.6053
   421.4  724.73   424.3  724.65   429.8725.5811   432.4  726.96   439.7  732.98
     443  733.99   446.9  734.26   472.1  733.33   497.2  733.34   544.3  734.79
   584.1  735.03   634.6  736.26   703.1  736.18   757.3  735.06   839.6  736.27
#Mann= 4 ,-1,0
       0     .08       0     210     .07       0   418.7    .045       0
   429.8     .07       0
Bank Sta=418.7,429.8
XS Rating Curve= 0 ,0
Exp/Cntr=0.3,0.1

Type RM Length L Ch R = 1 ,5159    ,367.1,372,373.9
XS GIS Cut Line= 3
1622843.48753881 522979.405632091622573.16805673523339.772015773
1622316.87032612523611.694968661
#Sta/Elev= 30
       0  733.91    41.5  735.18    50.9  734.23   111.8  733.17   126.7  731.91
   147.2  733.14     256  734.75     303  733.57   322.7  732.11   348.5  727.33
   381.8  726.57   392.7  723.58   403.6  717.81   407.1  716.75   418.8  715.63
  422.87  716.73   430.2  722.33   432.9  722.79   446.6  721.33     505  721.89
   519.5  721.24   545.4  723.97   590.9  725.56   602.5  727.18   676.1  727.03
   698.7  727.95   749.1  732.21   755.6  733.84   768.3  740.01   824.2  742.46
#Mann= 6 ,-1,0
       0     .07       0     320     .06       0   407.1    .045       0
  422.87     .06       0  550.48     .07       0  700.48     .08       0
Bank Sta=407.1,422.87
XS Rating Curve= 0 ,0
Exp/Cntr=0.3,0.1

Type RM Length L Ch R = 1 ,4787    ,68.6,68.5,68.7
XS GIS Cut Line= 3
     1622747.433      522877.1761622297.29478146523064.725311446
     1621977.641      523224.139
#Sta/Elev= 30
       0  728.06      41  727.53    51.7  726.41    68.7  727.66    90.8  726.87
   108.6  724.23   126.3  720.21     132  719.83   154.8  720.57   179.6  720.16
   190.3   719.3   232.3  719.36   257.9  718.29   357.8  717.94   410.5  716.09
   425.5  714.32   428.5  713.36   434.4709.5752   439.1  708.41   442.7  708.56
   445.2  709.61   449.8   714.6   453.3  715.86   562.2  718.17   705.9  722.47
   741.9  722.69   752.9  723.34   763.9  725.58   820.1  726.53   844.8  727.78
#Mann= 7 ,-1,0
       0     .07       0   434.4    .045       0   445.2     .07       0
     480     .08       0  507.65     .07       0  527.65     .08       0
  777.65     .07       0
Bank Sta=434.4,445.2
XS Rating Curve= 0 ,0
Exp/Cntr=0.3,0.1

Type RM Length L Ch R = 1 ,4718    ,260.2,262.2,261.1
XS GIS Cut Line= 3
1622738.79207758522806.8127129421622288.65385904522994.362024388
1621969.00007758523153.775712942
#Sta/Elev= 30
       0  724.34    81.4  722.37   217.5  718.04   280.5  716.89   294.7  716.19
   355.1  716.06   376.4   716.7   429.8  715.92   439.3  713.92   447.6  712.92
   455.1  710.64     460708.4957   461.7  707.72   465.2  707.32   468.9  707.56
   471.6708.5093   480.2  714.25   482.7  715.02   487.8  715.53   515.9  716.11
   548.9  717.37   614.9  718.09   666.2  719.87     774  720.55   776.4  720.76
   783.5  722.52   791.1  723.39   805.8  723.54   831.2  725.72   844.8  726.48
#Mann= 7 ,-1,0
       0     .07       0     170     .08       0     330     .07       0
     460    .045       0   471.6     .07       0  667.65     .08       0
  767.65     .07       0
Bank Sta=460,471.6
XS Rating Curve= 0 ,0
Exp/Cntr=0.3,0.1

Type RM Length L Ch R = 1 ,4456    ,192.8,192.5,160.8
XS GIS Cut Line= 3
1622713.09585486 522715.331270411622382.57100555522718.494187628
1621914.45925725 522878.22150715
#Sta/Elev= 30
       0   724.7    13.4  723.99    38.8  724.03    59.3  722.88     102  719.69
   115.3  719.59   131.5  717.06   144.8  716.25     164  716.32   197.1  714.32
   243.1  714.72   325.1  709.24     356  706.17   435.7  703.25   445.9  701.69
   451.4  700.91   456.2701.7242   463.4  706.11   470.4  707.18     547  709.18
   602.1  709.75   636.8  711.62   654.1  711.38   664.5  710.07   685.3  711.22
   735.7  711.78     772  711.19   789.3  711.85   810.7  710.58   825.2  710.54
#Mann= 6 ,-1,0
       0     .07       0     170     .08       0     260     .07       0
  440.54     .08       0   445.9    .045       0   456.2     .08       0
Bank Sta=445.9,456.2
XS Rating Curve= 0 ,0
Exp/Cntr(USF)=0,0
Exp/Cntr=0.3,0.1

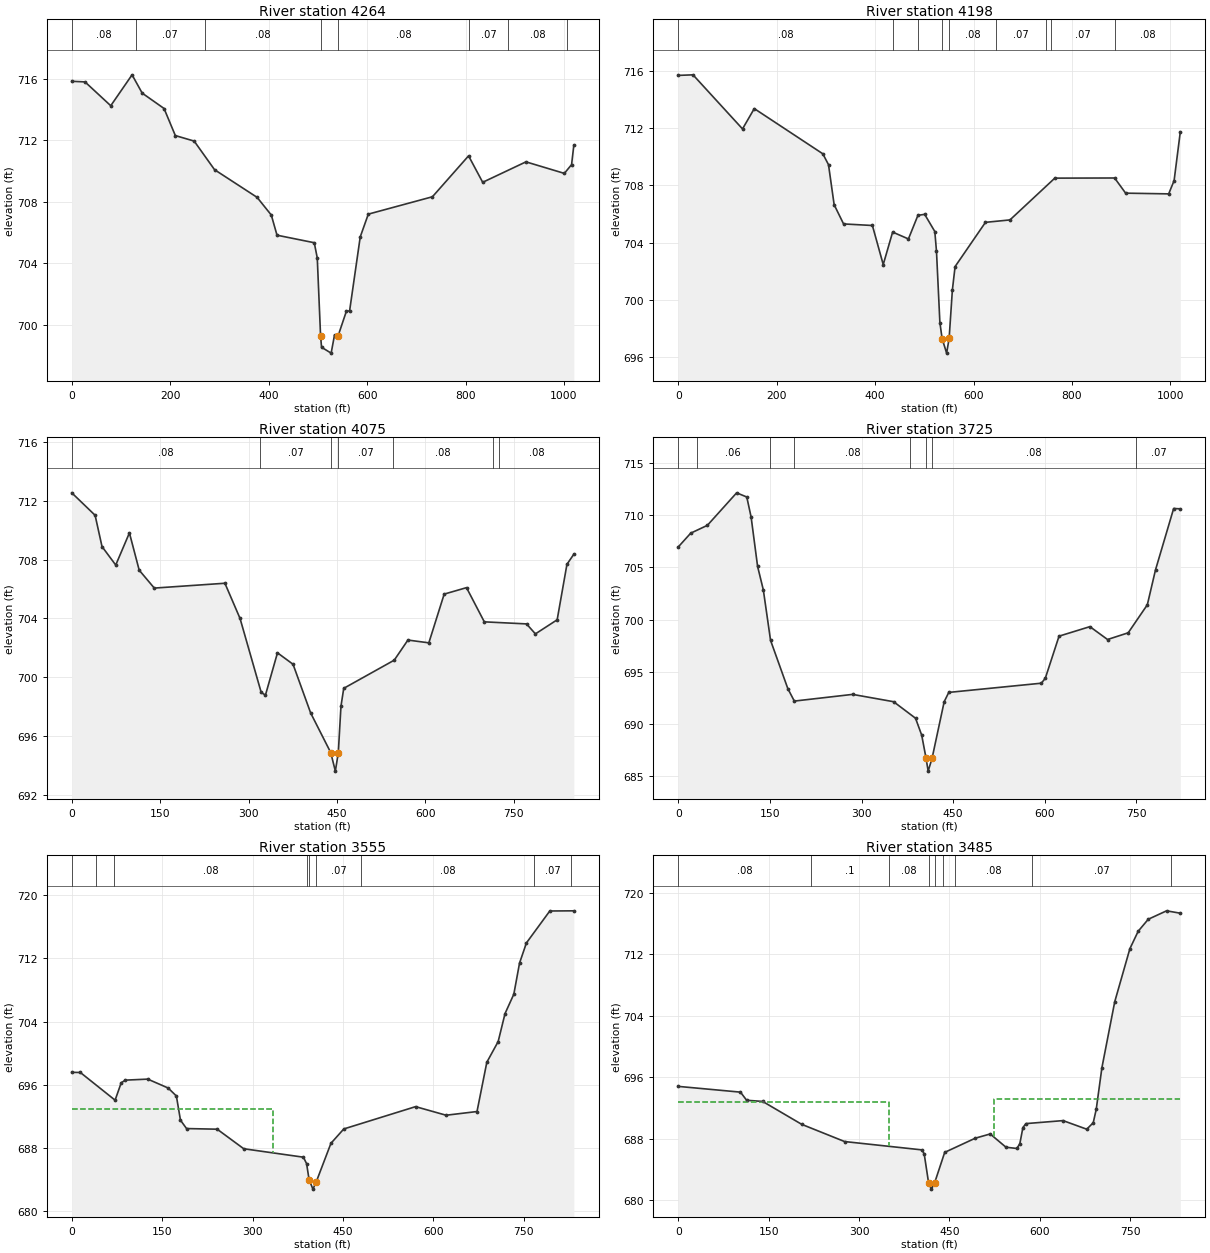
Type RM Length L Ch R = 1 ,4264    ,65.7,65.7,73.9
XS GIS Cut Line= 4
1622630.94186702522269.1106914361622273.53864951522482.927148903
1622203.32339361522712.731515955     1621878.638      522875.845
#Sta/Elev= 30
       0  715.83    26.9  715.79    79.2  714.24   122.5  716.25   143.1  715.06
   187.5  714.06   210.4   712.3   248.7  711.94   290.1  710.08   376.6  708.28
   405.4  707.13     417  705.82   492.7  705.33   498.8  704.34   505.5699.2775
   507.5  698.53     527  698.15   533.9  699.34   541.2  699.28   557.9  700.87
   564.5   700.9   586.1  705.71   602.5  707.19   732.8  708.32   806.2  710.98
   834.9  709.26   922.8  710.59  1000.8  709.84  1015.5  710.41  1020.1  711.68
#Mann= 8 ,-1,0
       0     .08       0     130     .07       0     270     .08       0
   505.5    .045       0   541.2     .08       0  806.77     .07       0
  886.77     .08       0 1006.77     .07       0
Bank Sta=505.5,541.2
XS Rating Curve= 0 ,0
Exp/Cntr=0.3,0.1

Type RM Length L Ch R = 1 ,4198    ,119.7,123.4,126.9
XS GIS Cut Line= 4
1622584.40398726522208.9389627111622227.00076975522422.755420178
1622156.78551385 522652.559787231621832.10012025522815.673271275
#Sta/Elev= 30
       0  715.68      30  715.72   130.6  711.94   154.5  713.36   293.8   710.2
   305.3  709.44   316.8  706.64   335.9   705.3   394.5  705.19   416.5  702.46
   435.6  704.73   467.7  704.25     487   705.9   500.7  705.97   521.3  704.77
   524.7  703.39   531.6  698.41   536.1 697.291   545.3  696.27   550.4697.2967
     557  700.69   562.5  702.32   624.2  705.41     674  705.58   765.1   708.5
   886.6  708.51     909  707.45   996.5   707.4  1007.5  708.33  1020.1  711.74
#Mann= 9 ,-1,0
       0     .08       0  436.48     .07       0  486.48     .08       0
   536.1    .045       0   550.4     .08       0  646.48     .07       0
  746.77     .08       0  756.77     .07       0  886.77     .08       0
Bank Sta=536.1,550.4
XS Rating Curve= 0 ,0
Exp/Cntr=0.3,0.1

Type RM Length L Ch R = 1 ,4075    ,350.7,350,346
XS GIS Cut Line= 3
     1622433.073      522197.294      1622091.68      522483.048
     1621753.017      522708.004
#Sta/Elev= 30
       0  712.56    39.6  711.03    51.3   708.9    74.6  707.64    97.8  709.83
   114.4  707.29     140  706.07   259.8   706.4   285.5     704   321.4  698.96
   328.6  698.78     349  701.66   375.4  700.88   405.3  697.56   439.3694.8675
   447.2   693.6   452.2  694.86   456.7  698.02   461.4  699.24   547.1  701.16
   570.3  702.53   605.8  702.34   631.8  705.66   669.7   706.1   699.9  703.77
   771.5  703.63   786.6  702.95   823.5  703.91   840.1  707.69   851.8  708.38
#Mann= 7 ,-1,0
       0     .08       0     320     .07       0   439.3    .045       0
   452.2     .07       0   545.2     .08       0   715.2      .1       0
   725.2     .08       0
Bank Sta=439.3,452.2
XS Rating Curve= 0 ,0
Exp/Cntr=0.3,0.1

Type RM Length L Ch R = 1 ,3725    ,170.6,169.6,168.2
XS GIS Cut Line= 3
     1622020.954      521897.158     1621868.737       522277.76
     1621667.517      522637.126
#Sta/Elev= 30
       0  706.94    20.4  708.26    47.7  709.01    95.6  712.12   112.2  711.72
   119.3   709.8   129.9  705.08   139.3  702.83   151.1  698.01   179.4  693.39
     190   692.2   285.4  692.84   352.5  692.14   388.4  690.56   398.5  688.94
   405.6686.7463   409.1   685.5   415.5686.7333   435.3  692.14   442.8  693.03
   594.3  693.91   600.8  694.38   623.3  698.41   673.8  699.32   702.7  698.09
   736.5  698.73   767.8  701.41   781.2  704.75   810.9  710.62   821.8  710.59
#Mann= 8 ,-1,0
       0     .07       0      30     .06       0     150     .07       0
     190     .08       0     380     .07       0   405.6    .045       0
   415.5     .08       0  749.91     .07       0
Bank Sta=405.6,415.5
XS Rating Curve= 0 ,0
Exp/Cntr=0.3,0.1

Type RM Length L Ch R = 1 ,3555    ,69.4,70,69.8
XS GIS Cut Line= 3
 1621818.6716946521813.6025371431621689.42397655522314.866909527
1621448.78832761522518.971781837
#Sta/Elev= 30
       0  697.56    14.3  697.54    71.9  694.03    82.1  696.24    88.9  696.57
   126.1   696.7     160  695.57   173.6  694.56   180.4  691.49   190.5  690.43
   241.3  690.35   285.4  687.87   384.4   686.8   389.7  685.98   393.8  683.96
   400.2  682.75   405.9  683.71   430.1  688.56   451.4  690.38   570.6  693.21
   621.2  692.12   672.5  692.59   688.8  698.84   707.6  701.46     719  705.01
   733.6  707.47   743.1  711.42   754.5  713.97   793.3  718.02   833.2  718.04
#Mann= 9 ,-1,0
       0     .08       0      40     .07       0      70     .08       0
     390     .07       0   393.8    .045       0   405.9     .07       0
     480     .08       0  767.66     .07       0  827.66     .08       0
#XS Ineff= 2 , 0
          334.65  692.89
Permanent Ineff=
       F       F
Bank Sta=393.8,405.9
XS Rating Curve= 0 ,0
Exp/Cntr=0.3,0.1

Type RM Length L Ch R = 1 ,3485    ,172,174.8,177.8
XS GIS Cut Line= 3
1621766.31599158521756.9457553061621637.06827353 522258.21012769
1621396.43262459      522462.315
#Sta/Elev= 30
       0  694.81   103.3  694.06   113.5     693   140.1  692.85     205  689.86
   276.1  687.62   404.9  686.53   408.3  685.95   415.4  682.27   420.2  681.42
   425.6  682.27   442.2  686.21     493  688.06   517.7  688.61   543.9  686.88
   561.9  686.72   566.9  687.34     572  689.45   577.1  689.96   638.6  690.35
   677.9  689.23   688.7  690.07   693.7  691.83   703.1  697.25   724.4  705.85
   749.5  712.75   763.3  715.03     780  716.59   810.4  717.69   833.2  717.38
#Mann= 9 ,-1,0
       0     .08       0     220      .1       0     350     .08       0
   415.4    .045       0   425.6     .08       0     440     .07       0
     460     .08       0  587.66     .07       0  817.66     .08       0
#XS Ineff= 2 , 0
          349.92  692.84  524.02           693.2
Permanent Ineff=
       F       F
Bank Sta=415.4,425.6
XS Rating Curve= 0 ,0
Exp/Cntr=0.3,0.1

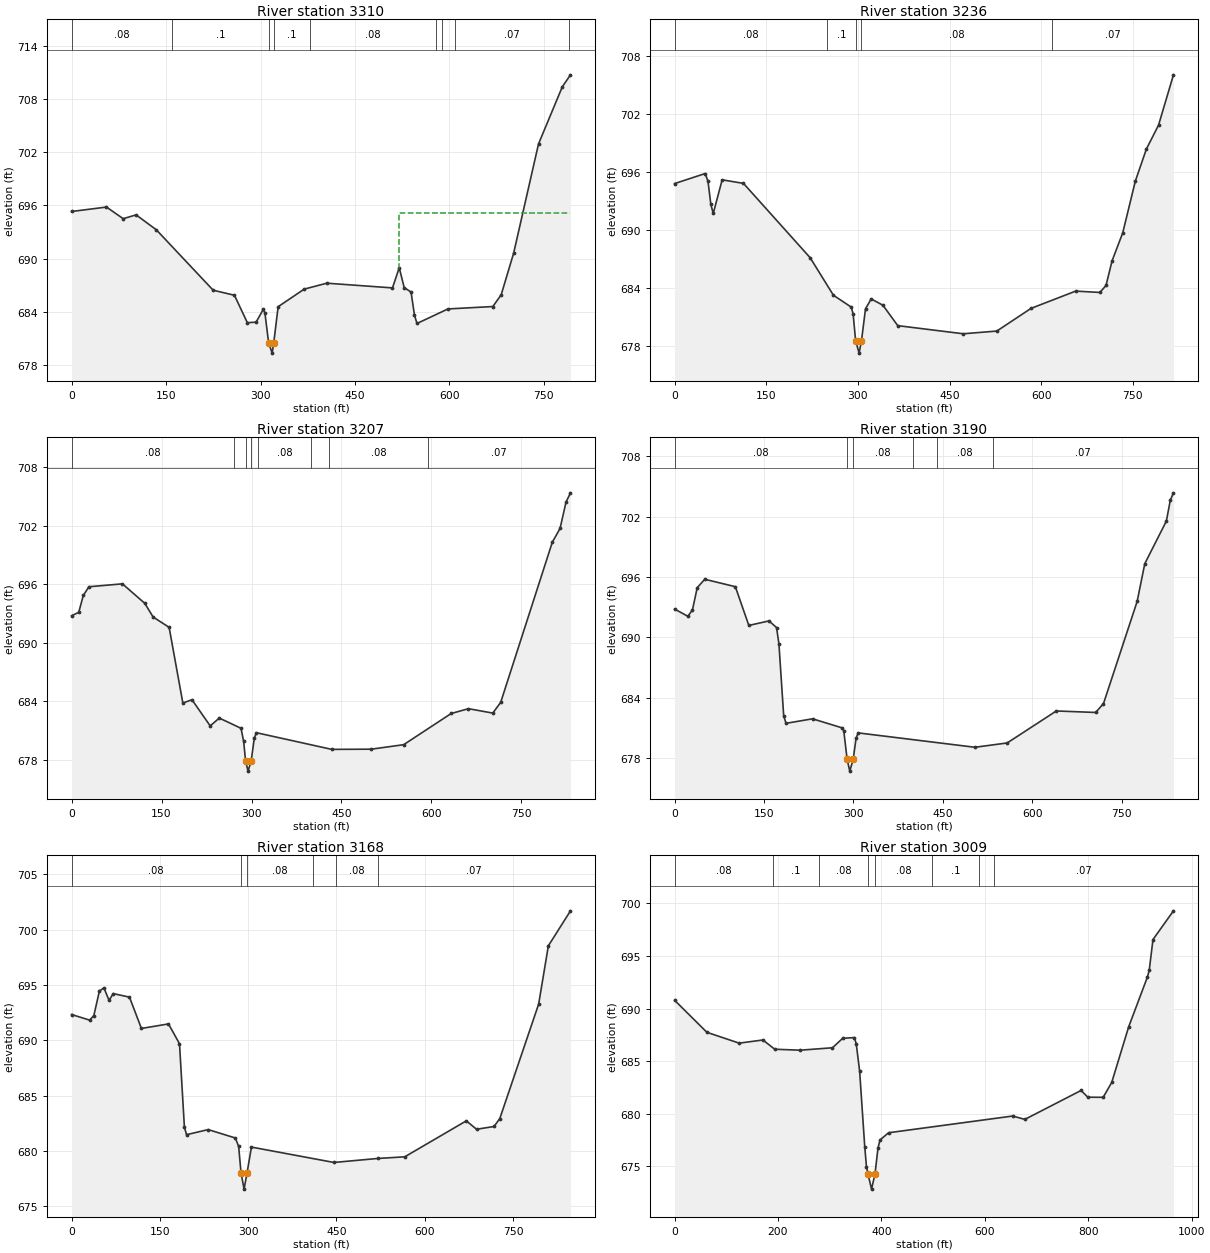
Type RM Length L Ch R = 1 ,3310    ,74.6,74,73.3
XS GIS Cut Line= 5
1621742.47785003521749.4223498151621614.54658359521978.252733103
1621548.77590793522033.5427704631621393.93939223522243.741932211
1621374.67326213522425.866251427
#Sta/Elev= 30
       0  695.31    55.4  695.81    81.9   694.5   102.4  694.93   134.5  693.25
   224.8  686.44   258.6  685.87   279.1  682.78     293  682.84   304.7  684.32
   307.1  683.82  312.87  680.52   318.5  679.35     321   680.5     328  684.58
   369.3  686.56   405.3  687.23   509.6   686.7   520.3  688.97   528.2  686.74
   539.1  686.23   544.5  683.64   548.5  682.69   597.7  684.33     669   684.6
   682.2  685.92     702  690.61   741.5  702.92   779.3  709.36   792.3  710.71
#Mann= 9 ,-1,0
       0     .08       0     160      .1       0  312.87    .045       0
     321      .1       0  378.09     .08       0  578.09     .07       0
  588.09     .08       0  608.09     .07       0  789.16     .08       0
#XS Ineff= 2 , 0
                          519.62           695.1
Permanent Ineff=
       F       F
Bank Sta=312.87,321
XS Rating Curve= 0 ,0
Exp/Cntr(USF)=0,0
Exp/Cntr=0.3,0.1

Type RM Length L Ch R = 1 ,3236    ,28.8,28.6,28.5
XS GIS Cut Line= 3
1621728.52066478521733.7206108791621379.67600202522116.750496717
 1621341.6060945522412.763451087
#Sta/Elev= 30
       0   694.8    50.1  695.84    54.7  695.04    59.4  692.64    63.3  691.71
    77.9  695.19   112.8  694.82   221.9  687.14     260  683.26   289.3  682.03
   292.3   681.3   296.3  678.56     302  677.28  305.91  678.55   312.5  681.86
   321.8  682.88     341  682.23   365.3  680.12   472.5  679.28   527.4  679.56
   583.3   681.9   656.5  683.69   696.1  683.55   706.1  684.27     716  686.81
   733.5  689.71   754.1  695.05   772.2  698.37   792.1  700.84   816.5  706.04
#Mann= 5 ,-1,0
       0     .08       0     250      .1       0   296.3    .045       0
  305.91     .08       0  618.08     .07       0
Bank Sta=296.3,305.91
XS Rating Curve= 0 ,0
Exp/Cntr(USF)=0,0
Exp/Cntr=0.3,0.1

Type RM Length L Ch R = 1 ,3207    ,18.1,17.6,17.2
XS GIS Cut Line= 3
1621697.79785673521710.1528379621621358.85015887522109.050468777
1621325.41654241522415.717433508
#Sta/Elev= 30
       0  692.79    11.9  693.14    19.5  694.87    28.8  695.76    84.7  696.06
   121.9  694.07   135.9  692.66   162.6   691.6   185.5  683.84   200.7  684.18
   231.1   681.5   246.3   682.3   282.5  681.25   286.9   679.9  290.07  677.93
   294.2  676.86   299.5677.9288   304.7  680.26   308.1   680.8   433.8  679.09
   499.7  679.11   553.7  679.57     633  682.77   661.8  683.26   702.3  682.81
   715.5  683.91   801.6  700.33   814.5  701.74   824.4  704.43   831.9  705.39
#Mann= 8 ,-1,0
       0     .08       0     270      .1       0  290.07    .045       0
   299.5      .1       0     310     .08       0     400      .1       0
     430     .08       0  593.45     .07       0
Bank Sta=290.07,299.5
XS Rating Curve= 0 ,0
Exp/Cntr(USF)=0,0
Exp/Cntr=0.3,0.1

Type RM Length L Ch R = 1 ,3190    ,21.3,21.5,21.4
XS GIS Cut Line= 4
1621666.43013237521681.6943158991621402.49379436522051.545021305
1621349.81980416522113.8475903621621319.23490662 522413.46630883
#Sta/Elev= 30
       0  692.81    22.3  692.09      30  692.72      38  694.93    50.6  695.77
     102  695.03   124.6  691.18   158.5  691.63   171.1  690.97   175.1  689.36
   183.1   682.2     187  681.45   231.5   681.9   281.1     681   283.9  680.72
  289.55  677.86     294   676.7   299.7  677.87   304.6  679.98   308.1   680.5
     504  679.07   558.1   679.5   640.6  682.68   706.5  682.53   719.7  683.41
   776.2  693.57     789  697.32   825.2  701.55   831.8  703.62   837.1  704.36
#Mann= 6 ,-1,0
       0     .08       0  289.55    .045       0   299.7     .08       0
     400      .1       0     440     .08       0  534.37     .07       0
Bank Sta=289.55,299.7
XS Rating Curve= 0 ,0
Exp/Cntr(USF)=0,0
Exp/Cntr=0.3,0.1

Type RM Length L Ch R = 1 ,3168    ,162.5,159.5,156.1
XS GIS Cut Line= 3
1621652.56113622 521669.177523661621337.08358199522103.596346089
1621307.06507145522412.843643412
#Sta/Elev= 30
       0  692.34    30.7  691.83    37.8  692.25    47.2  694.46    54.9  694.75
    63.6  693.62    70.7  694.23    98.3  693.91   118.6  691.08   164.6  691.49
   183.3   689.7   191.6  682.19   195.2  681.48   232.1  681.94   278.2  681.18
   283.8  680.42   287.8678.0519     293  676.56  298.15  678.05   305.5  680.36
   445.7  678.97     520  679.33     566  679.48   670.6  682.73     688  681.97
   717.7  682.22   727.5  682.94   793.5  693.28     810  698.55   847.6  701.71
#Mann= 6 ,-1,0
       0     .08       0   287.8    .045       0  298.15     .08       0
     410      .1       0     450     .08       0     520     .07       0
Bank Sta=287.8,298.15
XS Rating Curve= 0 ,0
Exp/Cntr(USF)=0,0
Exp/Cntr=0.3,0.1

Type RM Length L Ch R = 1 ,3009    ,348.1,346.5,343.1
XS GIS Cut Line= 3
1621358.54840133      521453.3331621346.75340133       521831.15
1621294.45740133      522415.617
#Sta/Elev= 30
       0   690.8    62.5  687.75   124.9  686.72   170.8  687.02   193.8  686.14
     243  686.05   305.4  686.28   325.1  687.18   347.8  687.25   351.4  686.64
   357.9  684.06   367.8  676.86   371.1  674.98  374.06  674.28   380.9  672.84
   387.6674.2761   393.4  676.75   397.4  677.52   413.9   678.2   653.9  679.79
   677.4  679.47   786.1  682.22   799.2  681.58   828.9  681.57   845.4  682.98
   878.2  688.27   914.5  693.01     918  693.66   925.2  696.57   964.8   699.3
#Mann= 8 ,-1,0
       0     .08       0     190      .1       0     280     .08       0
  374.06    .045       0   387.6     .08       0     498      .1       0
     588     .08       0     618     .07       0
Bank Sta=374.06,387.6
XS Rating Curve= 0 ,0
Exp/Cntr=0.3,0.1

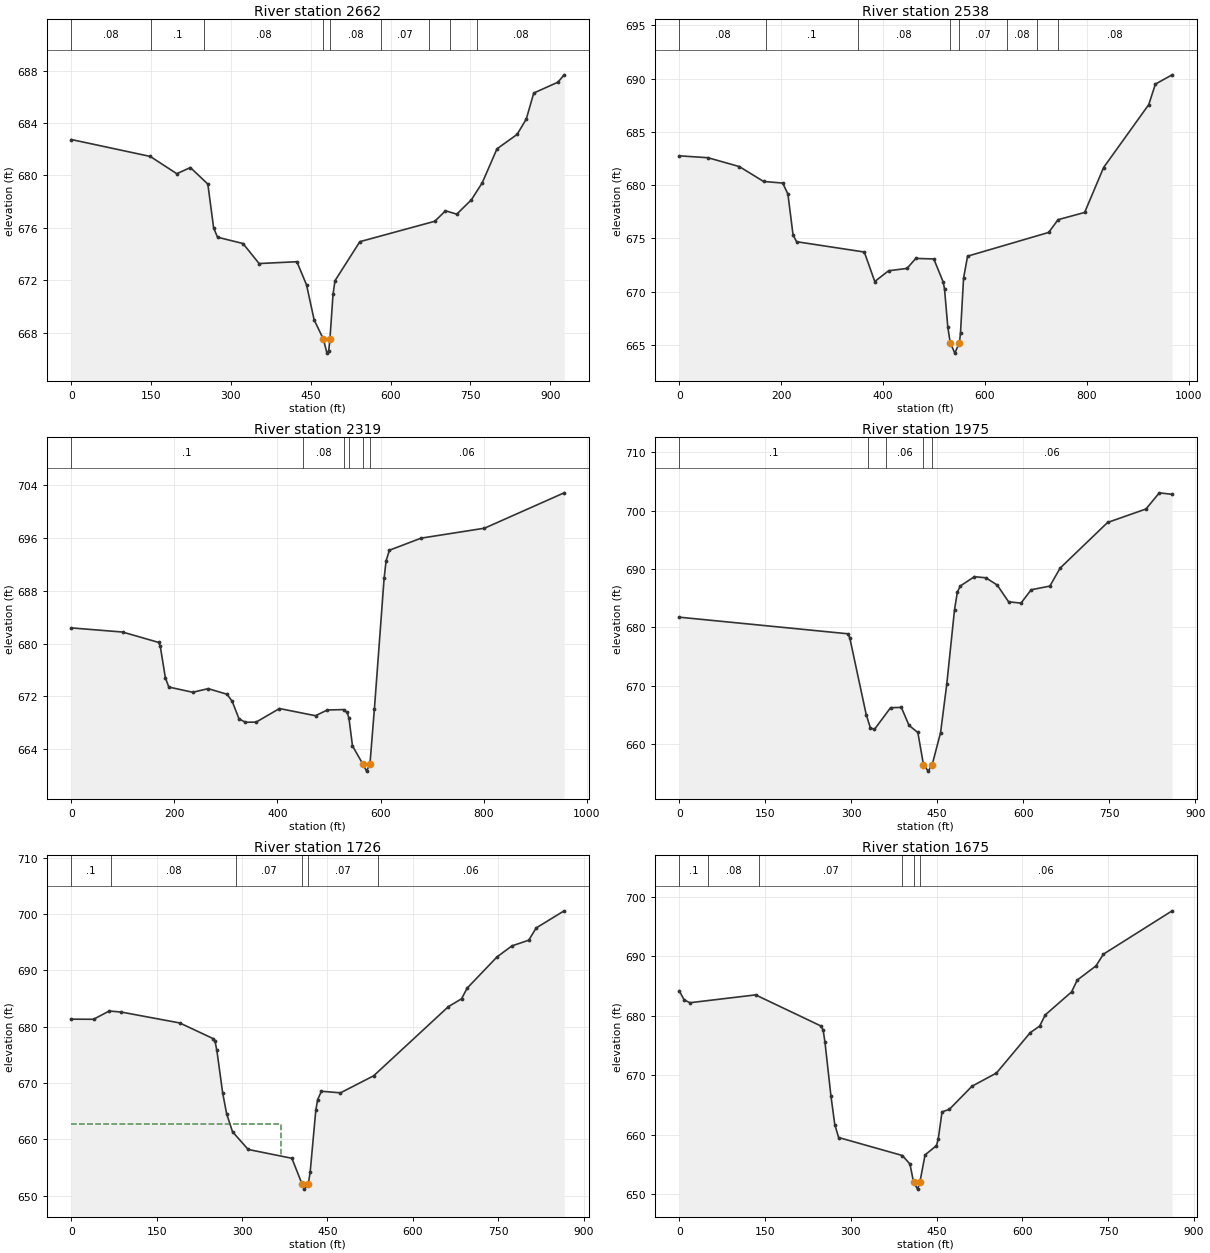
Type RM Length L Ch R = 1 ,2662    ,122.8,124,125.8
XS GIS Cut Line= 3
      1620899.95      521569.9641621095.42483451521977.109317964
     1621236.621      522430.272
#Sta/Elev= 30
       0  682.74   148.3  681.45   198.3  680.13   223.8   680.6   256.6  679.34
   267.5     676   274.8  675.28   322.7   674.8     353  673.27     424  673.41
   442.2  671.63   456.4  668.97   473.8667.5017   480.5  666.43   483.9  666.63
   486.1667.4957   491.9  670.91   495.6  671.96   542.3  674.94   683.3   676.5
   703.3   677.3   724.5  677.04     752  678.14   772.3  679.43   800.1  682.03
   837.9  683.13   855.1   684.3   869.2  686.29   914.7  687.12   926.3  687.68
#Mann= 9 ,-1,0
       0     .08       0     150      .1       0     250     .08       0
   473.8    .045       0   486.1     .08       0  581.64     .07       0
  671.64     .08       0  711.64     .07       0  761.64     .08       0
Bank Sta=473.8,486.1
XS Rating Curve= 0 ,0
Exp/Cntr=0.3,0.1

Type RM Length L Ch R = 1 ,2538    ,214.5,219.5,221.6
XS GIS Cut Line= 3
1620874.18811621521576.3623515451621008.00338807522050.607781812
1621149.19955356522503.770463849
#Sta/Elev= 30
       0  682.75    56.4  682.57   117.8  681.74   165.5  680.34     203  680.19
   213.2  679.16   223.4  675.29   230.3  674.68   363.2  673.71   383.7  670.94
   410.9  671.95     447  672.17   464.2  673.11   499.6  673.06     518   670.9
   520.6  670.25   527.1  666.65   531.8665.1983   540.8  664.21   549.9665.1988
     552  666.11     558  671.25   565.9  673.32     725  675.55   743.6  676.75
   795.7  677.43   832.9  681.65   921.5  687.56   934.6  689.49   967.4  690.36
#Mann= 8 ,-1,0
       0     .08       0     170      .1       0     350     .08       0
   531.8    .045       0   549.9     .07       0  642.76     .08       0
  702.76     .07       0  742.76     .08       0
Bank Sta=531.8,549.9
XS Rating Curve= 0 ,0
Exp/Cntr=0.3,0.1

Type RM Length L Ch R = 1 ,2319    ,342.8,344.3,344.3
XS GIS Cut Line= 3
      1620816.64      521594.7671620878.01061703521979.017861673
     1620721.427      522524.087
#Sta/Elev= 30
       0  682.37    99.5  681.74   169.2  680.17   172.5  679.64   182.5   674.8
   189.2  673.39   235.7   672.6   265.6  673.15   302.1   672.3     312  671.25
   325.4  668.56   337.8  668.05   358.6  668.07   403.9  670.13   473.8  669.04
   496.7  669.91   528.4  669.97   535.3  669.53   538.7  668.66   545.5  664.47
   565.9661.6625   572.8  660.63   579.4  661.68   588.1  670.11   606.9  689.88
   610.7  692.53   617.2  694.16   678.6  695.99   801.6   697.5   956.2  702.87
#Mann= 6 ,-1,0
       0      .1       0  449.12     .08       0  529.12     .07       0
  539.12     .06       0   565.9    .045       0   579.4     .06       0
Bank Sta=565.9,579.4
XS Rating Curve= 0 ,0
Exp/Cntr=0.3,0.1

Type RM Length L Ch R = 1 ,1975    ,250.8,249.1,244.8
XS GIS Cut Line= 3
     1620734.978      521559.947     1620555.845      521955.332
     1620381.155      522343.522
#Sta/Elev= 30
       0  681.76   293.7  678.92   297.3  678.27   326.1  665.07   333.3   662.8
   340.5  662.54   368.6  666.25   387.4   666.3   400.8  663.22   416.2     662
     426656.4929   434.2  655.38   441.1  656.45   455.8  661.97   466.6  670.23
   480.2  683.07   485.1  686.03   490.1   687.1   514.9   688.7   534.9  688.51
   554.6  687.27   574.5   684.4   596.1  684.17   613.9  686.46   646.5  687.09
   664.4  690.17   747.2  697.99   814.2   700.3   837.5  703.07   859.8  702.81
#Mann= 5 ,-1,0
       0      .1       0     330     .08       0     360     .06       0
     426    .045       0   441.1     .06       0
Bank Sta=426,441.1
XS Rating Curve= 0 ,0
Exp/Cntr=0.3,0.1

Type RM Length L Ch R = 1 ,1726    ,49.5,50.8,52.3
XS GIS Cut Line= 4
1620461.25110727521488.2976927881620345.48751095521858.119651528
1620351.70300605 521898.520369711620347.81832161522335.935837716
#Sta/Elev= 30
       0  681.35    39.1  681.33    66.6   682.8    87.3  682.62   190.4  680.68
   248.9  677.91   252.3  677.52   255.7  675.79     266  668.19   272.9  664.53
   283.2  661.35   310.7   658.2   387.5  656.63  405.21   652.1   409.6  651.15
   416.3  652.11   419.6  654.15   429.5  665.13   432.8  667.07   439.4  668.54
   472.9  668.26   531.2  671.29   662.5  683.58   685.5  684.96   695.3  686.85
   747.8   692.4     774  694.37   803.6  695.38   816.7  697.56   865.8   700.6
#Mann= 6 ,-1,0
       0      .1       0      70     .08       0     290     .07       0
  405.21    .045       0   416.3     .07       0  538.39     .06       0
#XS Ineff= 2 , 0
          369.14  662.64
Permanent Ineff=
       F       F
Bank Sta=405.21,416.3
XS Rating Curve= 0 ,0
Exp/Cntr(USF)=0,0
Exp/Cntr=0.3,0.1

Type RM Length L Ch R = 1 ,1675    ,51.4,50.2,49
XS GIS Cut Line= 4
 1620394.4345349521481.3052607951620300.42517144521865.112083521
1620294.20967633521924.1592870181620313.63309853522331.274216388
#Sta/Elev= 30
       0  684.19     8.5  682.67    18.6  682.19   133.5  683.51   248.3  678.25
   251.7  677.54   254.7  675.65   265.2  666.56     272  661.68   278.7   659.5
   390.2  656.47   403.5  655.03   409.8651.9991   416.7  650.81   420.8651.9429
   429.9  656.57   449.9  658.14     453  659.27   459.6  663.81   472.5  664.25
   512.1  668.14   554.8  670.35   613.9  677.15   630.4  678.26   640.2  680.14
   686.2  684.01   696.1     686   728.9  688.39     742  690.37   862.1  697.66
#Mann= 6 ,-1,0
       0      .1       0      50     .08       0     140     .07       0
     390     .06       0   409.8    .045       0   420.8     .06       0
Bank Sta=409.8,420.8
XS Rating Curve= 0 ,0
Exp/Cntr(USF)=0,0
Exp/Cntr=0.3,0.1

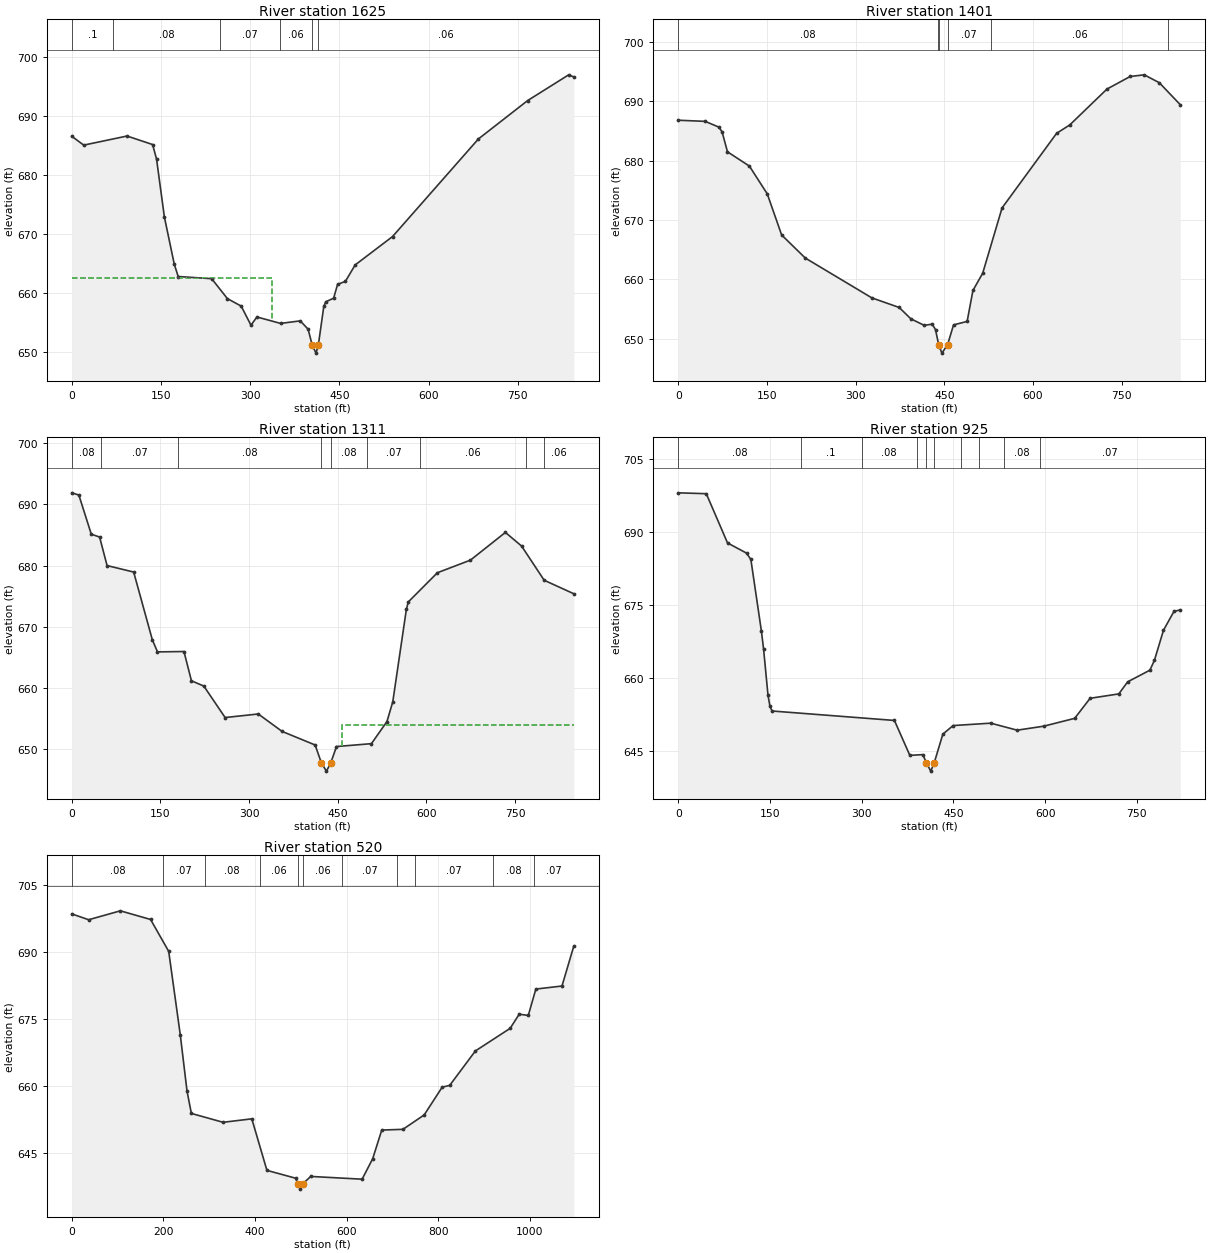
Type RM Length L Ch R = 1 ,1625    ,222.2,223.4,224.5
XS GIS Cut Line= 3
     1620196.508      521492.646     1620250.095      521898.392
     1620289.258      522331.397
#Sta/Elev= 30
       0  686.53    20.1  685.03    92.9  686.57   135.9  685.13   142.5  682.68
   155.7  672.86   172.3  664.88   178.9  662.79   235.2  662.42   261.6  659.05
   284.8  657.78   301.2  654.55   311.3  655.94     351  654.85   384.1  655.28
   397.3  653.87   404.1   651.2   410.6  649.82   414.6 651.265   423.7  657.75
     427  658.51   440.2  659.12   446.8  661.45     460  661.97   476.4  664.75
   539.3  669.56   683.6  686.08   766.3  692.57   835.3  696.93     844  696.57
#Mann= 6 ,-1,0
       0      .1       0      70     .08       0     250     .07       0
     350     .06       0   404.1    .045       0   414.6     .06       0
#XS Ineff= 2 , 0
          335.78  662.61
Permanent Ineff=
       F       F
Bank Sta=404.1,414.6
XS Rating Curve= 0 ,0
Exp/Cntr=0.3,0.1

Type RM Length L Ch R = 1 ,1401    ,90.3,89.7,90.5
XS GIS Cut Line= 3
1619849.19449938521605.4583900681620048.20576416521854.895264752
1620070.25110929522384.679336884
#Sta/Elev= 30
       0  686.79    45.6   686.6    68.9  685.62    74.2  684.82    83.3  681.47
   120.4  679.06   150.6  674.38   174.9  667.46   214.9  663.57   327.5  656.86
   373.8  655.24   393.5  653.33   416.3  652.22   429.6  652.44   435.2  651.51
   440.6  648.95     446  647.55   455.6648.9609   465.7  652.31   488.7  652.89
   498.5  658.11     515  661.01   547.8  672.02   640.1  684.59   662.2  685.99
   725.2  692.04   764.5  694.16   788.3  694.44   813.8  693.11   849.3   689.4
#Mann= 6 ,-1,0
       0     .08       0   439.1     .07       0   440.6    .045       0
   455.6     .07       0   529.1     .06       0   829.1      .1       0
Bank Sta=440.6,455.6
XS Rating Curve= 0 ,0
Exp/Cntr=0.3,0.1

Type RM Length L Ch R = 1 ,1311    ,387.3,386.9,381.6
XS GIS Cut Line= 3
     1619770.245      521666.0171619969.25626478521915.453874684
 1619991.3016099522445.237946816
#Sta/Elev= 30
       0  691.88      12  691.52      33  685.12    47.1  684.65    59.7  679.99
   104.7  678.93   136.3  667.85     145  665.88   189.8  665.94   202.4  661.16
   223.4  660.29   259.4  655.15   315.5  655.73   355.8  652.88   411.7  650.66
   422.4647.6875   430.8  646.39     438647.7073   447.8  650.41   506.9  650.88
   533.2   654.5     543  657.72     566  672.83   569.3  674.05   618.5  678.82
   674.4  680.88   733.5  685.41   760.9  683.18   799.1  677.59   849.3  675.38
#Mann= 9 ,-1,0
       0     .08       0      50     .07       0     180     .08       0
   422.4    .045       0     438     .08       0   499.1     .07       0
   589.1     .06       0   769.1      .1       0   799.1     .06       0
#XS Ineff= 2 , 0
                          456.83          653.92
Permanent Ineff=
       F       F
Bank Sta=422.4,438
XS Rating Curve= 0 ,0
Exp/Cntr=0.3,0.1

Type RM Length L Ch R = 1 ,925     ,401,404.3,406.6
XS GIS Cut Line= 3
     1619489.216       521787.29     1619622.443      522177.324
     1619793.851      522548.707
#Sta/Elev= 30
       0  697.96    45.9  697.78    80.6  687.67   111.8  685.57   118.8  684.27
   136.1   669.5   139.6  665.86   146.8  656.41     150  654.11   153.4  653.15
   353.6  651.21   378.8  644.04   400.1  644.19   405.8642.5458     413   640.8
   418.7  642.51   432.8   648.4   449.6  650.16   511.1  650.65   554.4  649.21
   597.8  650.03   648.4  651.64   673.7  655.76   720.6  656.66   735.1  659.14
   771.5  661.54   778.9  663.58   793.7  669.74   810.8   673.6   821.2  673.92
#Mann= 10 ,-1,0
       0     .08       0     200      .1       0     300     .08       0
     390     .07       0   405.8    .045       0   418.7     .07       0
  462.16     .08       0  492.16     .07       0  532.16     .08       0
  592.16     .07       0
Bank Sta=405.8,418.7
XS Rating Curve= 0 ,0
Exp/Cntr=0.3,0.1

Type RM Length L Ch R = 1 ,520     ,,,
XS GIS Cut Line= 2
1619300.92600978521810.532736316 1619184.2201742522900.810937147
#Sta/Elev= 30
       0  698.56    36.9  697.25   106.1  699.25   172.1  697.31   211.7  690.15
     237   671.4   251.7  658.79   261.2  653.77   330.5  651.78   393.2  652.56
   426.2  640.99   488.9  639.23   493.4638.0276   498.8  636.78   504.8638.0145
   521.9  639.63   634.1  639.01   657.2  643.61     677  650.04   723.2   650.2
   769.6  653.43   808.9  659.66   825.4  660.07   881.5   667.8   957.4  672.87
   977.2  676.05     997  675.76  1013.5  681.69  1070.6  682.37  1096.5  691.37
#Mann= 11 ,-1,0
       0     .08       0     200     .07       0     290     .08       0
     410     .06       0   493.4    .045       0   504.8     .06       0
     590     .07       0     710     .08       0     750     .07       0
     920     .08       0    1010     .07       0
Bank Sta=493.4,504.8
XS Rating Curve= 0 ,0
Exp/Cntr(USF)=0,0
Exp/Cntr=0.3,0.1
LCMann Table=0

Chan Stop Cuts=-1
Use User Specified Reach Order=0
Composite Channel Slope=5